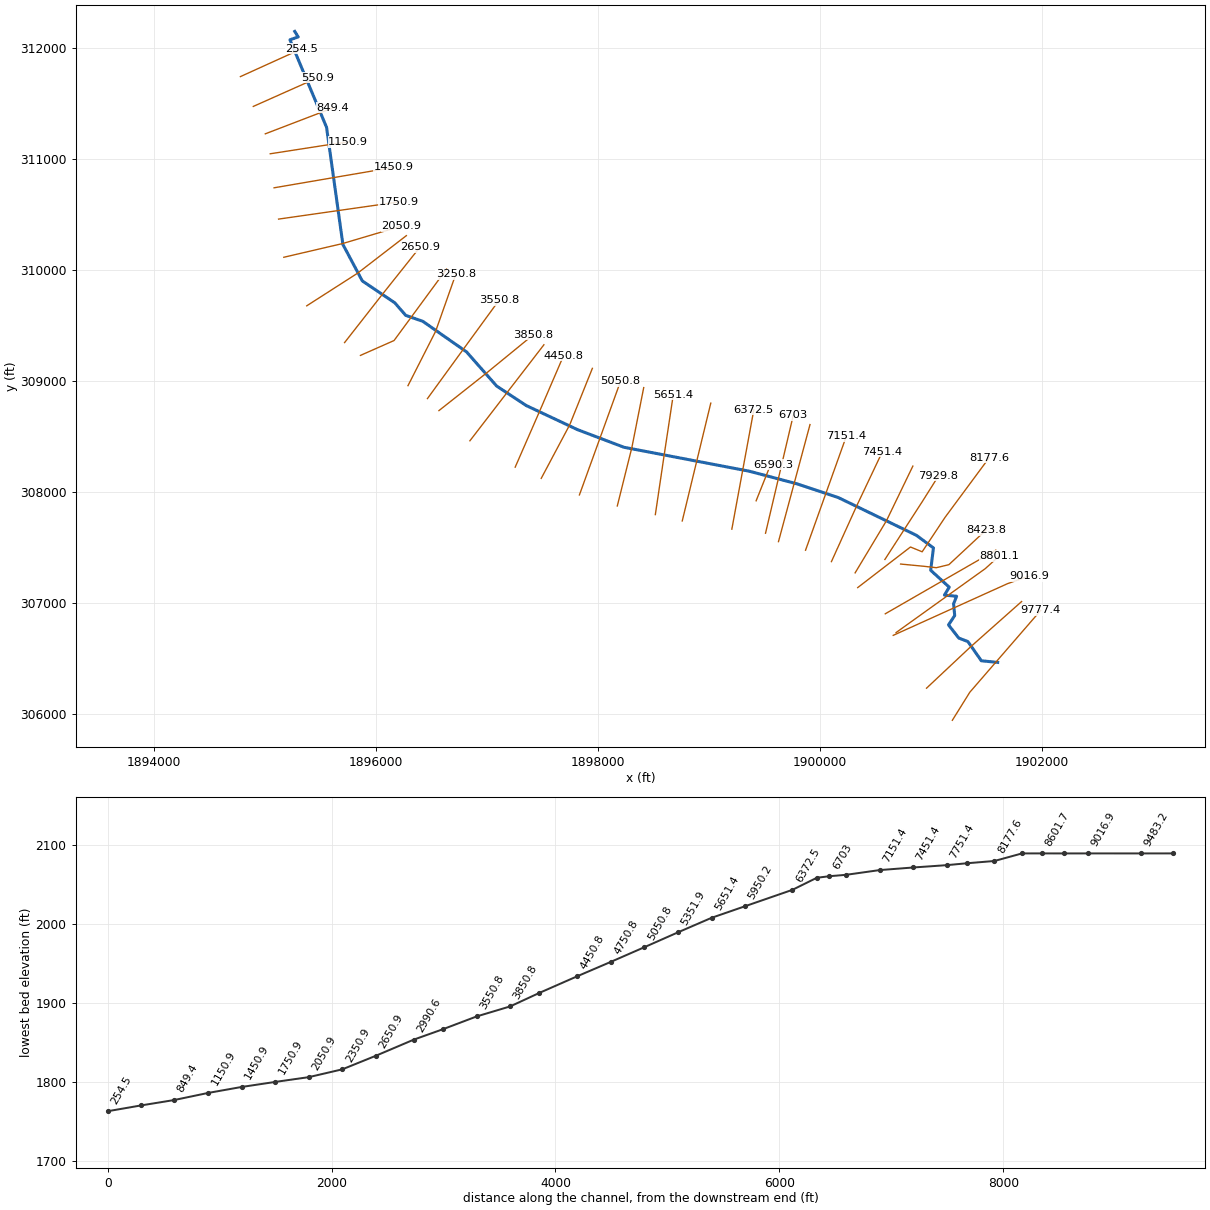
--- SndBrnch.prj (project) ---

Proj Title=SndBrnch
Current Plan=p01
Default Exp/Contr=0,0
English Units
Geom File=g01
Flow File=f01
Plan File=p01
BEGIN DESCRIPTION:
END DESCRIPTION:
DSS Export Rating Curves= 0
DSS Export Rating Curve Sorted= 0
DSS Export Volume Flow Curves= 0
DXF OffsetX= 0
DXF OffsetY= 0
DXF ScaleX= 0
DXF ScaleY= 0

--- SndBrnch.p01 (plan) ---

Plan Title=Floodplain
Program Version=4.00
Geom File=g01
Flow File=f01
K Sum by GR=0
Std Step Tol=0.01
Critical Tol=0.01
Num of Std Step Trials=20
Max Error Tol=0.3
Flow Tol Ratio=0.001
Split Flow NTrial=30
Split Flow Tol=0.02
Split Flow Ratio=0.02
Log Output Level=0
Friction Slope Method=1
Unsteady Friction Slope Method=2
Unsteady Bridges Friction Slope Method=1
Global Log Level=0
CheckData=False
Run HTab=0
Run UNet=0
Run PostProcess=0
UNET Theta=0
UNET Theta Warmup=0
UNET ZTol=0
UNET ZSATol=0
UNET MxIter=0
UNET MaxInSteps=0
UNET DtIC=0
UNET DtMin=0
UNET MaxCRTS=0
UNET WFStab=0
UNET SFStab=0
UNET WFX=0
UNET SFX=0
UNET DSS MLevel=0
UNET DZMax Abort=0
UNET Convert EG Bridges=0
UNET Use Existing IB Tables=0
UNET Froude Limit=0
UNET Froude Power=0
Write IC File=0
Echo Input=False
Echo Output=False
Write Detailed=0

--- SndBrnch.f01 (steady flow) ---

Flow Title=NFF Regression Equation
Program Version=4.00
Number of Profiles=1
Profile Names=P100yr
River Rch & RM=SndBrnch,Main      ,9777.4
809.0687
River Rch & RM=SndBrnch,Main      ,8423.8
897.6510
River Rch & RM=SndBrnch,Main      ,7929.8
1016.146
River Rch & RM=SndBrnch,Main      ,6590.3
1068.822
River Rch & RM=SndBrnch,Main      ,4111.3
1165.353
River Rch & RM=SndBrnch,Main      ,254.5
1285.856
Boundary for River Rch & Prof#=SndBrnch,Main      ,1
Up Type=0
Dn Type=3
Dn Slope=0.025512

--- SndBrnch.g01 (geometry) ---

Geom Title=USGS 3m DEM
Program Version=4.10

River Reach=SndBrnch        ,Main
Reach XY= 30
     1901600.825      306466.221     1901453.622      306480.943
      1901332.49      306654.181     1901250.432      306685.443
     1901157.955      306803.975     1901213.965      306888.638
     1901203.547       306992.84     1901230.901      307061.873
     1901121.489      307072.296     1901164.474      307143.934
     1900997.491       307296.03     1901022.506       307496.92
     1900870.112      307610.243     1900164.151      307951.517
      1899795.54      308073.962     1899363.104      308188.592
      1898235.17      308403.885     1897817.017      308562.446
     1897355.907      308779.162     1897088.915       308954.52
     1896816.694      309263.223     1896423.287       309538.24
     1896268.636      309592.268     1896171.001      309704.685
     1895877.588       309902.78     1895703.057      310231.019
     1895555.893      311286.064     1895226.371      312074.096
     1895300.615      312100.145     1895269.356      312149.641

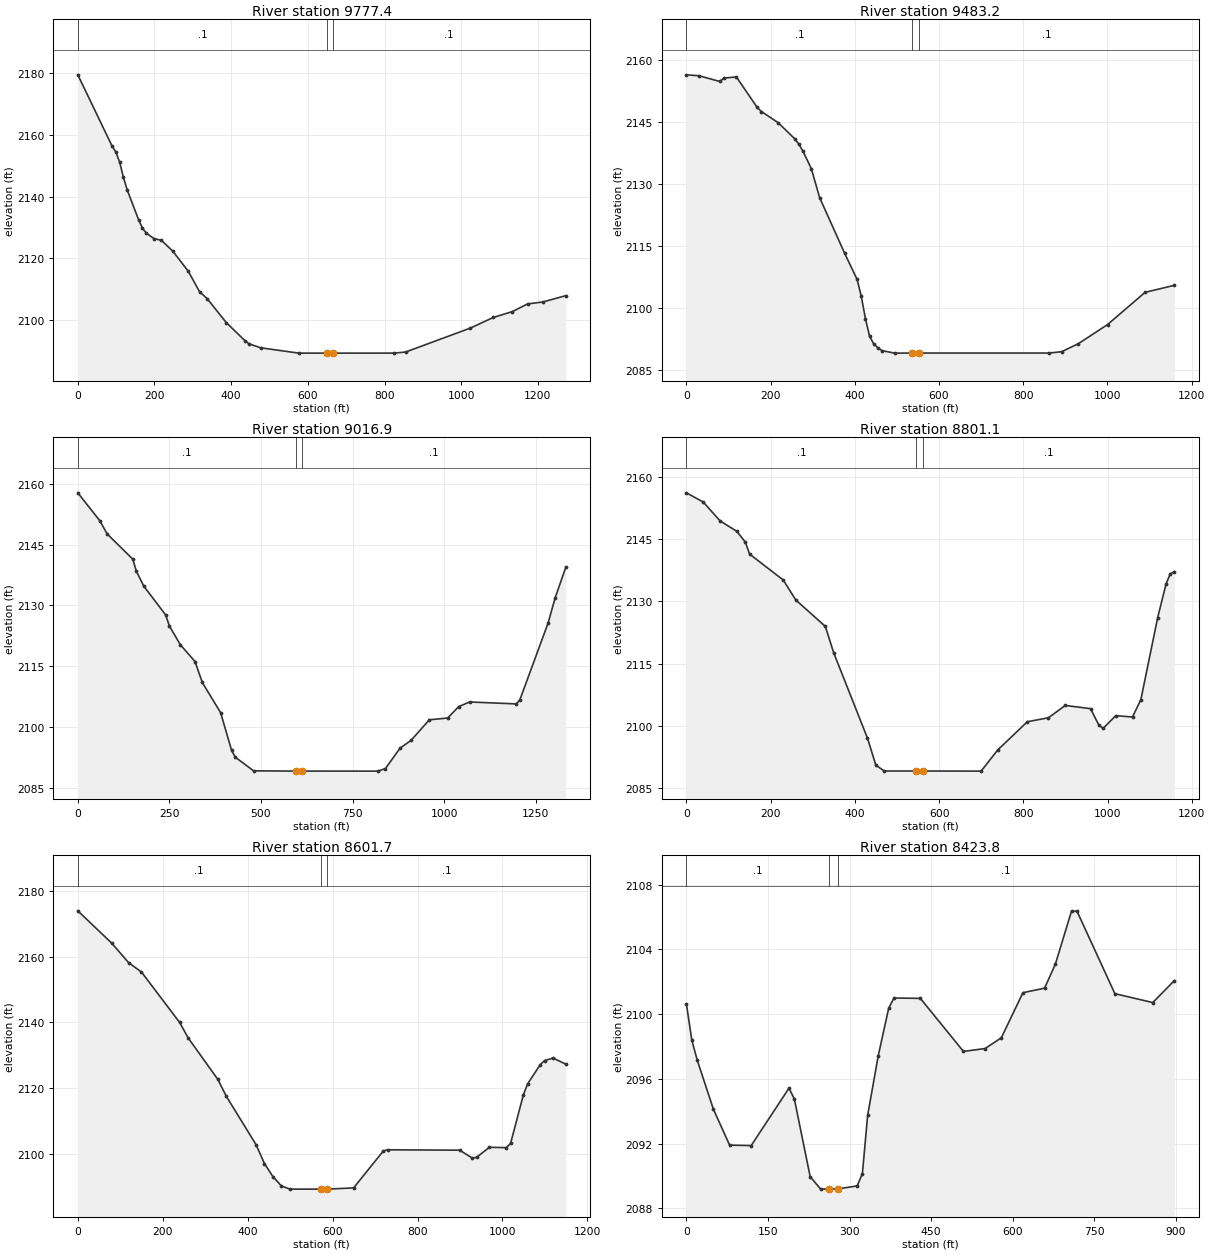
Type RM Length L Ch R = 1 ,9777.4  ,295.6,294.1,292.1
XS GIS Cut Line= 3
     1901192.585      305944.892     1901349.823       306197.54
     1901988.222      306934.516
#Sta/Elev= 30
       0 2179.53    89.3 2156.42    99.2 2154.47   109.1 2151.18     119 2146.23
     129 2142.11   158.7 2132.44   168.6 2129.77   178.6 2128.15   198.4  2126.4
   218.2  2125.8     248 2122.26   287.7 2115.85   317.5 2109.15   337.4 2106.89
   387.1 2099.13   436.9 2093.12   446.8 2092.21   476.7 2090.94   576.2  2089.2
   649.8  2089.2   664.8  2089.2   824.9 2089.21   854.7 2089.55  1023.9 2097.33
  1083.6 2100.78  1133.3 2102.68  1173.1 2105.17  1212.9  2105.8  1272.6 2107.85
#Mann= 3 , 0 , 0
       0      .1       0   649.8    .045       0   664.8      .1       0
Bank Sta=649.8,664.8
XS Rating Curve= 0 ,0
Exp/Cntr=0.3,0.1

Type RM Length L Ch R = 1 ,9483.2  ,475.8,466.3,454.4
XS GIS Cut Line= 3
     1900959.955       306234.06     1901356.481      306606.198
       1901816.5      307014.463
#Sta/Elev= 30
       0 2156.38    29.7 2156.16    79.1 2154.78      89 2155.58   118.6 2155.88
   168.1  2148.5     178 2147.52   217.5 2144.86   257.1 2140.95     267 2139.64
   276.8 2137.93   296.6 2133.74   316.4 2126.72   375.7 2113.31   405.4 2106.96
   415.3 2102.89   425.2 2097.48     435 2093.26   444.9 2091.39   454.8 2090.45
   464.7 2089.78   494.4 2089.18   536.3  2089.2   551.3  2089.2   861.2  2089.2
     891 2089.52   930.7 2091.45  1000.1 2096.07  1089.4 2103.86  1158.9 2105.55
#Mann= 3 , 0 , 0
       0      .1       0   536.3    .045       0   551.3      .1       0
Bank Sta=536.3,551.3
XS Rating Curve= 0 ,0
Exp/Cntr=0.3,0.1

Type RM Length L Ch R = 1 ,9016.9  ,222.8,215.7,204.5
XS GIS Cut Line= 3
     1900660.067      306709.919     1901689.363       307175.48
     1901880.257      307242.762
#Sta/Elev= 30
       0 2157.76      60 2150.89      80 2147.65     150 2141.42     160 2138.41
     180 2134.78   239.9 2127.67   249.9 2124.96   279.9 2120.34   319.9  2116.2
   339.9 2111.03   389.9 2103.59   419.9  2094.3   429.9 2092.63   479.9 2089.26
   596.5  2089.2   611.5  2089.2   819.8 2089.19   839.8 2089.83   879.8 2094.85
   909.8 2096.77   959.7 2101.84  1009.7 2102.27  1039.7 2105.08  1069.7 2106.23
  1197.2 2105.75  1206.8 2106.75  1283.9 2125.67  1303.2  2131.9  1332.1 2139.39
#Mann= 3 , 0 , 0
       0      .1       0   596.5    .045       0   611.5      .1       0
Bank Sta=596.5,611.5
XS Rating Curve= 0 ,0
Exp/Cntr=0.3,0.1

Type RM Length L Ch R = 1 ,8801.1  ,203.8,199.4,227
XS GIS Cut Line= 3
      1900685.38      306734.763     1901489.783      307311.345
     1901615.073      307424.975
#Sta/Elev= 30
       0 2156.11      40 2153.89      80 2149.35     120 2146.83     140 2144.22
     150 2141.37   229.9 2135.14   259.9 2130.31   329.9 2123.98   349.9 2117.59
   429.9 2097.12   449.9  2090.6   469.9  2089.2   546.3  2089.2   561.3  2089.2
   699.8 2089.17   739.8 2094.32   809.8 2101.06   859.7    2102   899.7 2104.97
   959.7  2104.2   979.7 2100.18   989.7 2099.47  1019.6 2102.51  1059.4 2102.19
  1079.2 2106.36    1119    2126    1139 2134.17  1148.9  2136.6  1158.8 2137.15
#Mann= 3 , 0 , 0
       0      .1       0   546.3    .045       0   561.3      .1       0
Bank Sta=546.3,561.3
XS Rating Curve= 0 ,0
Exp/Cntr=0.3,0.1

Type RM Length L Ch R = 1 ,8601.7  ,191.4,177.2,163
XS GIS Cut Line= 2
     1900588.437      306904.169     1901584.212      307477.343
#Sta/Elev= 30
       0 2173.95    79.9  2164.1   119.9 2158.13   149.9 2155.32   239.8 2139.96
   259.8 2135.26   329.7 2122.63   349.7 2117.47   419.6 2102.77   439.6 2096.96
   459.6 2092.98   479.6 2090.15   499.6  2089.2   571.7  2089.2   586.7  2089.2
   649.4 2089.57   719.4 2100.82   729.3 2101.18   899.2 2101.06   929.2 2098.64
   939.2 2098.89   969.1 2101.94  1009.1 2101.83  1019.1 2103.13    1049 2117.81
    1059 2121.21    1089 2127.11    1099 2128.34    1119 2129.11    1149 2127.27
#Mann= 3 , 0 , 0
       0      .1       0   571.7    .045       0   586.7      .1       0
Bank Sta=571.7,586.7
XS Rating Curve= 0 ,0
Exp/Cntr=0.3,0.1

Type RM Length L Ch R = 1 ,8423.8  ,219.6,246.2,272.6
XS GIS Cut Line= 5
     1900726.478      307352.263     1900933.942      307332.232
     1901048.404      307319.355     1901161.436       307346.54
      1901496.24      307658.451
#Sta/Elev= 30
       0 2100.63     9.9  2098.4    19.8 2097.17    49.6 2094.13    79.4 2091.91
   119.1 2091.88   188.6 2095.43   198.5 2094.76   227.6 2089.96   246.8 2089.19
   262.9  2089.2   277.9  2089.2     314 2089.39   323.6 2090.14   333.3 2093.75
   352.7 2097.42     372 2100.37   381.7    2101   430.2 2100.98   509.5  2097.7
   549.3 2097.88   579.1 2098.54   618.9 2101.33   658.7 2101.61   678.6  2103.1
   708.4 2106.39   718.4 2106.36     788 2101.27   857.7 2100.72   897.4 2102.08
#Mann= 3 , 0 , 0
       0      .1       0   262.9    .045       0   277.9      .1       0
Bank Sta=262.9,277.9
XS Rating Curve= 0 ,0
Exp/Cntr=0.3,0.1

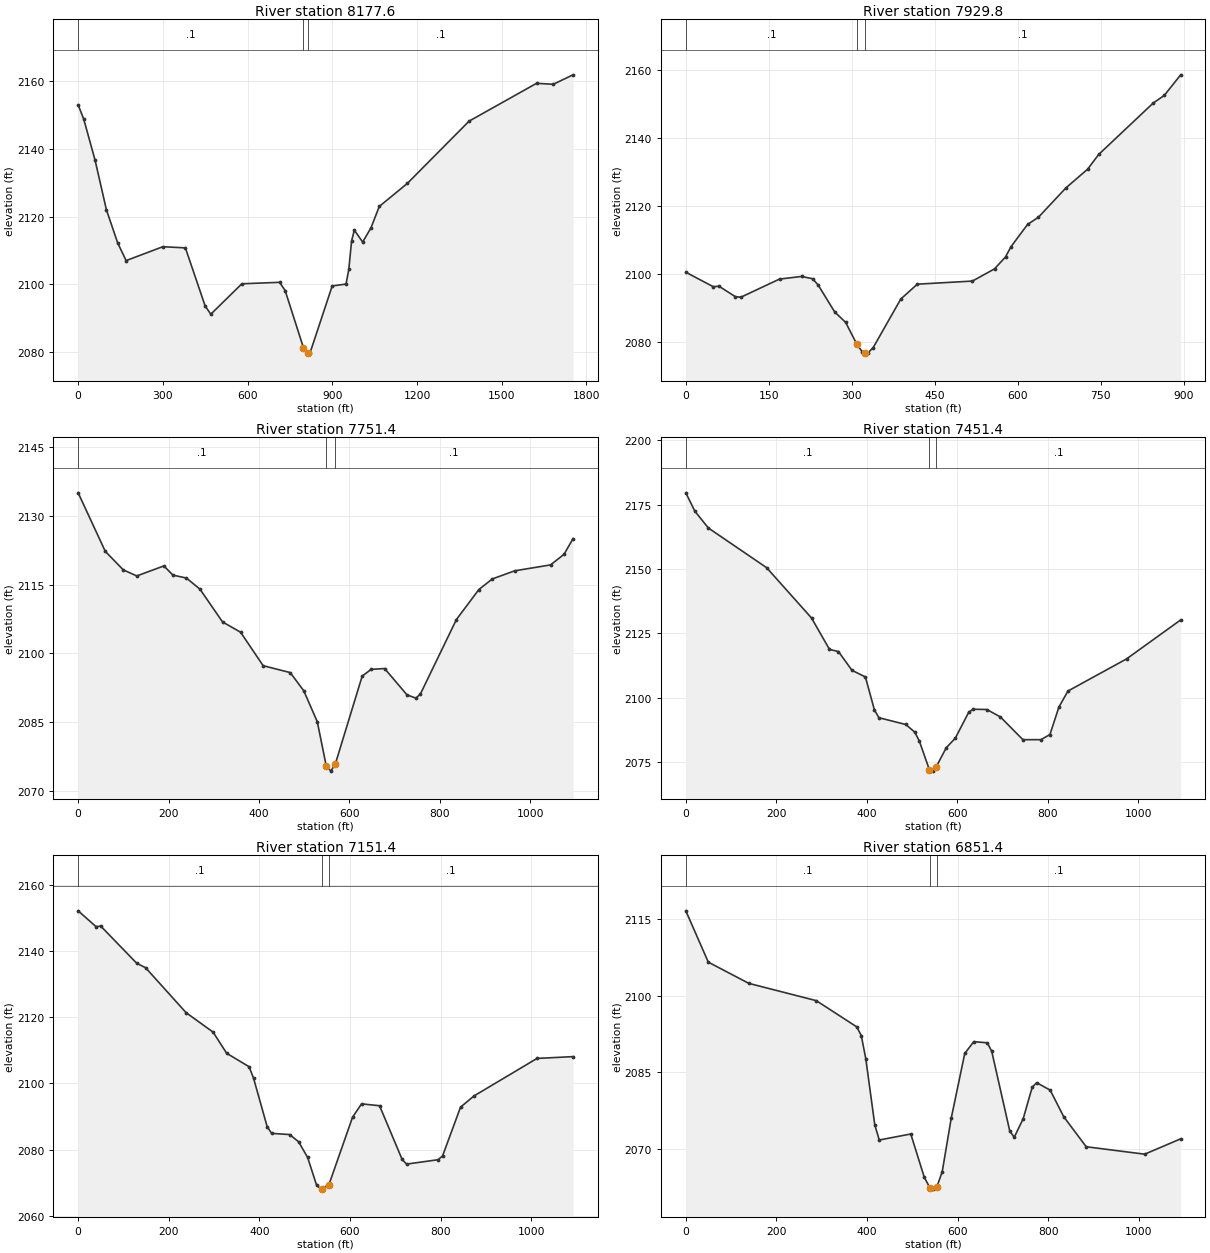
Type RM Length L Ch R = 1 ,8177.6  ,247.3,247.5,247.8
XS GIS Cut Line= 5
     1900340.134      307140.128      1900815.44      307505.801
     1900920.669      307462.583     1901126.958      307772.963
     1901523.534      308308.762
#Sta/Elev= 30
       0 2153.05      20 2148.77      60 2136.66     100 2122.04   139.9 2112.23
   169.9 2106.98   299.8 2111.09   379.8 2110.75   449.8 2093.56   469.8 2091.12
   579.7 2100.12   713.4 2100.56   733.1 2098.13   797.7 2081.27   811.5 2079.61
   812.7 2079.62   821.3 2079.69   899.8 2099.48   948.8 2100.04   958.6 2104.37
   968.4 2112.79   978.2 2115.99  1007.7 2112.47  1037.1 2116.67  1066.5    2123
  1165.7  2129.8  1384.6 2148.24  1623.4 2159.42  1683.1 2159.15  1752.7 2161.94
#Mann= 3 , 0 , 0
       0      .1       0   797.7    .045       0   812.7      .1       0
Bank Sta=797.7,812.7
XS Rating Curve= 0 ,0
Exp/Cntr=0.3,0.1

Type RM Length L Ch R = 1 ,7929.8  ,177.7,178.5,181.3
XS GIS Cut Line= 3
      1900584.83      307393.262     1900920.232      307912.186
     1901067.893      308146.335
#Sta/Elev= 30
       0  2100.5    49.8 2096.23    59.8  2096.4    89.7  2093.3    99.7 2093.16
   169.4 2098.49   209.3 2099.26   229.2 2098.59   239.2 2096.76   269.1 2088.82
     289 2085.74   309.4 2079.25   318.9  2077.1   324.4 2076.87   328.9 2076.69
   338.8 2078.33   388.7 2092.62   418.6 2096.99   518.2  2097.9   558.1 2101.49
     578    2105     588 2108.04   617.9 2114.57   637.6  2116.7   687.1 2125.31
   726.6 2130.86   746.4 2135.16   845.3 2150.34     865 2152.54   894.7 2158.61
#Mann= 3 , 0 , 0
       0      .1       0   309.4    .045       0   324.4      .1       0
Bank Sta=309.4,324.4
XS Rating Curve= 0 ,0
Exp/Cntr=0.3,0.1

Type RM Length L Ch R = 1 ,7751.4  ,297.4,300,300.2
XS GIS Cut Line= 3
      1900316.91      307272.713      1900599.46      307743.121
     1900836.786      308234.307
#Sta/Elev= 30
       0 2135.06    59.9  2122.3    99.8 2118.24   129.7 2116.92   189.6 2119.11
   209.5  2117.1   239.4 2116.46   269.4 2114.03   319.3 2106.88   359.2 2104.64
   409.1 2097.33   468.9 2095.83   498.9 2091.86   528.8  2085.1   548.7 2075.42
   558.7 2074.32   568.6 2075.85   628.1 2095.06   647.9 2096.53   677.7 2096.71
   727.3 2090.95   747.1 2090.25     757 2091.19   836.4  2107.4     886 2113.94
   915.7 2116.26   965.3 2118.04  1044.7 2119.33  1074.4 2121.64  1094.3 2125.05
#Mann= 3 , 0 , 0
       0      .1       0   548.7    .045       0   568.6      .1       0
Bank Sta=548.7,568.6
XS Rating Curve= 0 ,0
Exp/Cntr=0.3,0.1

Type RM Length L Ch R = 1 ,7451.4  ,298.2,300,302.2
XS GIS Cut Line= 3
     1900103.426      307374.065     1900328.554      307870.933
     1900563.087      308365.889
#Sta/Elev= 30
       0 2179.62    19.8 2172.54    49.6 2165.96   178.5 2150.51   277.7 2130.93
   317.4 2118.71   337.2 2117.88     367 2110.58   396.7    2108   416.6  2095.2
   426.5 2092.14     486  2089.5   505.8 2086.51   515.7 2083.16     538 2071.94
   545.5 2071.36     553 2072.97   575.4 2080.48   595.3 2084.17   625.2 2094.35
   635.1 2095.44     665 2095.33   694.9 2092.45   744.7 2083.59   784.5  2083.6
   804.4  2085.6   824.3 2096.33   844.2 2102.52   973.7 2115.02  1093.2 2130.19
#Mann= 3 , 0 , 0
       0      .1       0     538    .045       0     553      .1       0
Bank Sta=538,553
XS Rating Curve= 0 ,0
Exp/Cntr=0.3,0.1

Type RM Length L Ch R = 1 ,7151.4  ,298.2,300,301.8
XS GIS Cut Line= 3
     1899870.307      307476.751     1900054.221      307990.844
     1900238.136      308504.937
#Sta/Elev= 30
       0 2152.16    39.7 2147.35    49.6 2147.58     129 2136.35   148.9 2134.95
   238.2 2121.38   297.8 2115.51   327.6 2109.12   377.2 2105.05   387.2 2101.51
     417 2086.97   426.9 2084.91   466.6 2084.55   486.4 2082.38   506.3 2077.66
   526.2 2069.23   536.1 2068.06   538.5 2068.06   553.5 2069.45   605.6 2089.83
   625.4 2093.83   665.1 2093.26   714.8 2077.08   724.7 2075.62   794.2 2076.95
   804.1 2078.08   843.8 2092.83   873.6 2096.23  1012.6 2107.56    1092  2108.1
#Mann= 3 , 0 , 0
       0      .1       0   538.5    .045       0   553.5      .1       0
Bank Sta=538.5,553.5
XS Rating Curve= 0 ,0
Exp/Cntr=0.3,0.1

Type RM Length L Ch R = 1 ,6851.4  ,147.7,148.4,149.2
XS GIS Cut Line= 3
     1899626.463       307554.04     1899768.419      308081.264
     1899910.374      308608.487
#Sta/Elev= 30
       0 2116.63    49.6 2106.57     139 2102.41   287.9 2099.02   377.2 2093.88
   387.2 2092.17   397.1 2087.66     417 2074.66   426.9  2071.7   496.4 2072.88
   526.2  2064.4   538.5 2062.34     546 2062.07   553.5 2062.39   565.8 2065.48
   585.7 2075.98   615.5 2088.66   635.4 2090.98   665.1 2090.76     675 2089.11
   714.8 2073.48   724.7 2072.23   744.6 2075.91   764.4 2082.05   774.3 2082.94
   804.1 2081.47   833.9 2076.27   883.5 2070.38  1012.6 2068.92    1092 2071.93
#Mann= 3 , 0 , 0
       0      .1       0   538.5    .045       0   553.5      .1       0
Bank Sta=538.5,553.5
XS Rating Curve= 0 ,0
Exp/Cntr=0.3,0.1

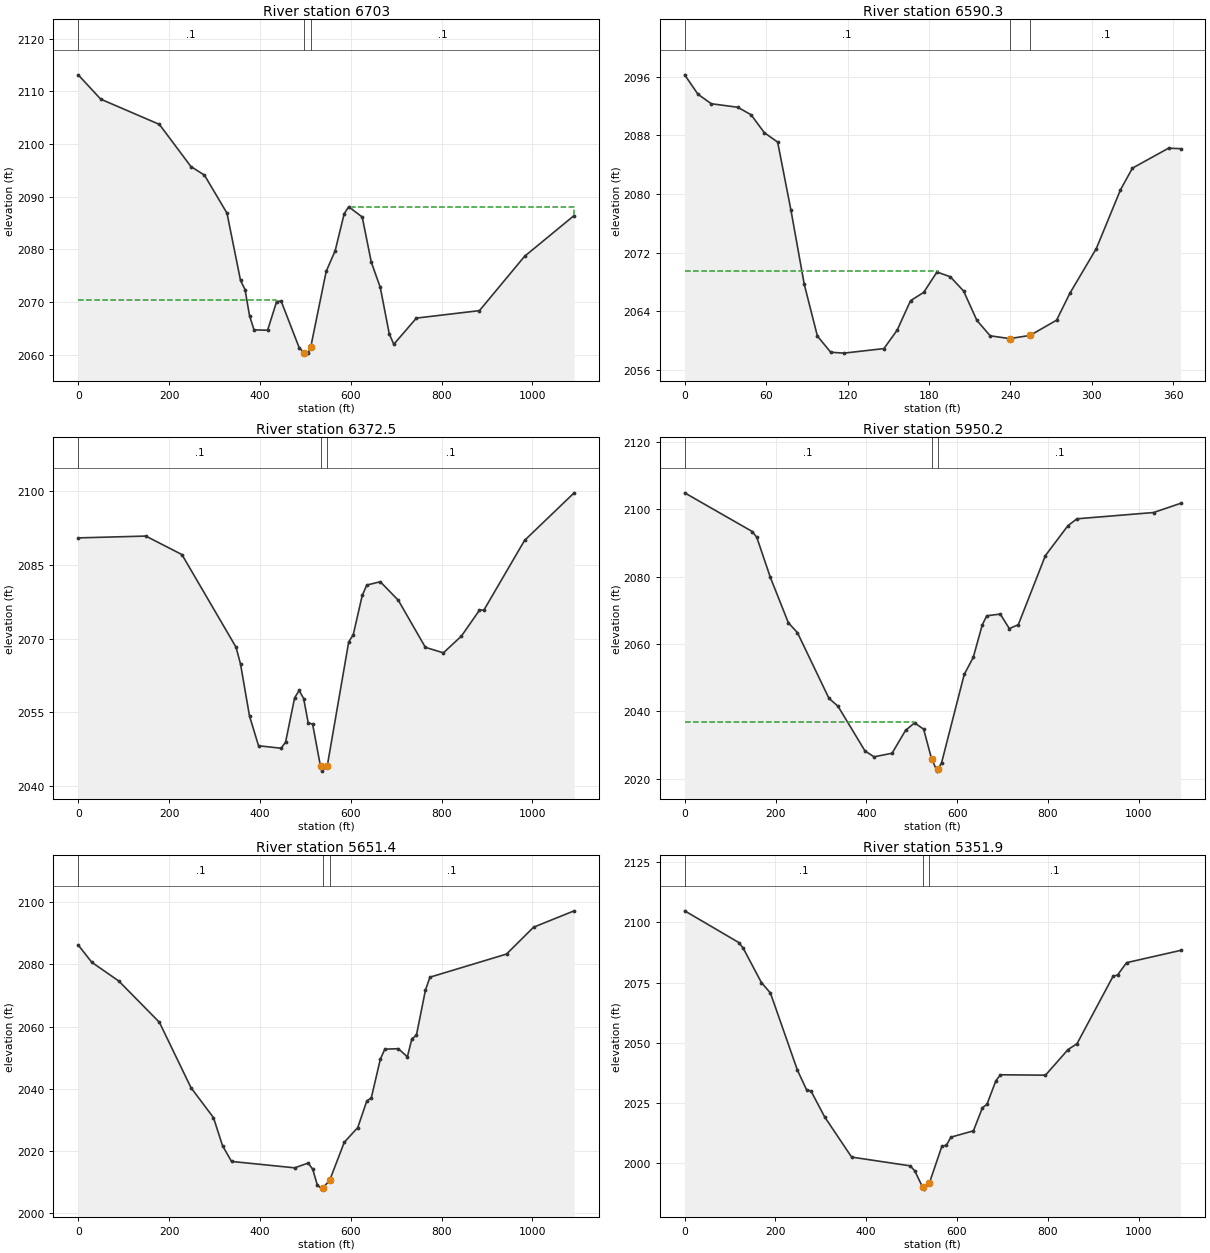
Type RM Length L Ch R = 1 ,6703    ,116,112.6,109.2
XS GIS Cut Line= 3
     1899509.803      307629.767     1899634.869       308161.25
     1899759.934      308692.733
#Sta/Elev= 30
       0 2113.15    49.6 2108.53   178.7 2103.74   248.2 2095.74     278  2094.1
   327.6 2086.88   357.4 2074.11   367.3 2072.39   377.2 2067.43   387.2 2064.72
     417 2064.66   436.8 2070.07   446.7 2070.22   486.4 2061.37   496.9 2060.39
   506.3 2060.31   511.9 2061.42     546 2075.83   565.8 2079.75   585.7  2086.8
   595.6 2088.09   625.4 2086.15   645.3 2077.59   665.1 2072.79     685 2063.93
   694.9 2061.99   744.6 2066.96   883.5 2068.38   982.8 2078.69    1092 2086.44
#Mann= 3 , 0 , 0
       0      .1       0   496.9    .045       0   511.9      .1       0
#XS Ineff= 2 , 0
          435.69 2070.31  602.33         2087.98
Permanent Ineff=
       F       F
Bank Sta=496.9,511.9
XS Rating Curve= 0 ,0
Exp/Cntr=0.3,0.1

Type RM Length L Ch R = 1 ,6590.3  ,213.4,217.8,222.3
XS GIS Cut Line= 3
     1899425.237      307922.105     1899537.896      308203.751
     1899583.794      308245.477
#Sta/Elev= 30
       0 2096.26     9.8 2093.61    19.6 2092.32    39.1 2091.84    48.9 2090.82
    58.7 2088.37    68.5 2087.09    78.3  2077.8    88.1  2067.7    97.8 2060.64
   107.6 2058.44   117.4 2058.32   146.8 2058.94   156.6 2061.47   166.4 2065.47
   176.1  2066.6   185.9 2069.38   195.7 2068.73   205.5 2066.79   215.3 2062.78
   225.1 2060.68   239.5  2060.3   254.5 2060.74     274 2062.81   283.8 2066.48
   303.3 2072.58   321.1 2080.59   329.9 2083.54   356.5 2086.26   365.4 2086.19
#Mann= 3 , 0 , 0
       0      .1       0   239.5    .045       0   254.5      .1       0
#XS Ineff= 2 , 0
           186.5 2069.56
Permanent Ineff=
       F       F
Bank Sta=239.5,254.5
XS Rating Curve= 0 ,0
Exp/Cntr=0.3,0.1

Type RM Length L Ch R = 1 ,6372.5  ,423.5,422.3,421
XS GIS Cut Line= 3
     1899206.374      307666.455     1899305.301      308203.419
     1899404.227      308740.382
#Sta/Elev= 30
       0 2090.51   148.9 2090.88   228.3 2087.12   347.4 2068.29   357.4 2064.84
   377.2 2054.25   397.1 2048.21   446.7 2047.71   456.6 2048.95   476.5 2057.97
   486.4 2059.46   496.4 2057.82   506.3 2052.93   516.2 2052.58   533.5 2044.01
   536.1 2043.05   548.5 2044.17   595.6 2069.35   605.6 2070.81   625.4  2078.8
   635.4 2080.91   665.1 2081.59   704.8 2077.82   764.4 2068.24   804.1 2067.12
   843.8 2070.53   883.5  2075.8   893.4 2075.84   982.8    2090    1092 2099.68
#Mann= 3 , 0 , 0
       0      .1       0   533.5    .045       0   548.5      .1       0
#XS Ineff= 2 , 0
          485.96 2059.33
Permanent Ineff=
       F       F
Bank Sta=533.5,548.5
XS Rating Curve= 0 ,0
Exp/Cntr=0.3,0.1

Type RM Length L Ch R = 1 ,5950.2  ,296.7,298.7,300.7
XS GIS Cut Line= 3
     1898759.687      307740.272     1898888.175      308270.938
     1899016.664      308801.604
#Sta/Elev= 30
       0 2104.83   148.9 2093.35   158.8 2091.64   188.6 2079.78   228.3  2066.3
   248.2  2063.4   317.7  2043.9   337.5 2041.58   397.1 2028.29     417 2026.57
   456.6 2027.62   486.4 2034.42   506.3 2036.63   526.2 2034.74   543.7 2025.95
   555.9 2022.32   558.7 2023.04   565.8 2024.87   615.5 2050.98   635.4 2056.05
   655.2 2065.66   665.1 2068.37   694.9 2068.89   714.8 2064.58   734.6 2065.73
   794.2 2086.21   843.8 2095.08   863.7 2097.13  1032.4 2098.99    1092 2101.72
#Mann= 3 , 0 , 0
       0      .1       0   543.7    .045       0   558.7      .1       0
#XS Ineff= 2 , 0
          505.51 2036.87
Permanent Ineff=
       F       F
Bank Sta=543.7,558.7
XS Rating Curve= 0 ,0
Exp/Cntr=0.3,0.1

Type RM Length L Ch R = 1 ,5651.4  ,301.7,299.5,297.8
XS GIS Cut Line= 3
     1898517.422      307797.599     1898597.447      308337.877
      1898679.04       308877.66
#Sta/Elev= 30
       0 2086.23    29.8 2080.68    89.4 2074.63   178.8 2061.35   248.3 2040.33
   297.9 2030.68   317.8 2021.66   337.6 2016.59   476.7 2014.53   506.4 2016.08
   516.4 2014.08   526.3 2009.12   536.2 2007.68   538.7  2008.1   553.7  2010.5
   585.9 2022.76   615.6 2027.49   635.5 2036.05   645.4 2037.04   665.3  2049.5
   675.2 2052.72     705 2052.86   724.8 2050.25   734.8 2056.06   744.7 2057.14
   764.5 2071.63   774.5 2075.87   943.2 2083.31  1002.8 2091.96  1092.1 2097.22
#Mann= 3 , 0 , 0
       0      .1       0   538.7    .045       0   553.7      .1       0
Bank Sta=538.7,553.7
XS Rating Curve= 0 ,0
Exp/Cntr=0.3,0.1

Type RM Length L Ch R = 1 ,5351.9  ,303.4,301.1,298.3
XS GIS Cut Line= 3
     1898174.795      307875.429     1898306.866      308406.033
     1898412.656      308941.544
#Sta/Elev= 30
       0 2104.76   119.3  2091.6   129.2 2089.18     169 2075.02   188.9 2070.67
   248.5 2038.61   268.4 2030.58   278.4 2029.97   308.2 2019.33   367.8  2002.6
   497.1 1998.96     507 1996.86   524.1 1990.15   526.9 1989.31   539.1 1991.83
   566.6 2007.08   576.6  2007.5   586.5 2010.86   636.1 2013.49     656  2023.1
   665.9 2024.46   685.7 2034.31   695.7 2036.75   794.9 2036.58   844.5  2047.2
   864.4 2049.66   943.8 2077.62   953.7 2078.16   973.6 2083.26  1092.6 2088.35
#Mann= 3 , 0 , 0
       0      .1       0   524.1    .045       0   539.1      .1       0
Bank Sta=524.1,539.1
XS Rating Curve= 0 ,0
Exp/Cntr=0.3,0.1

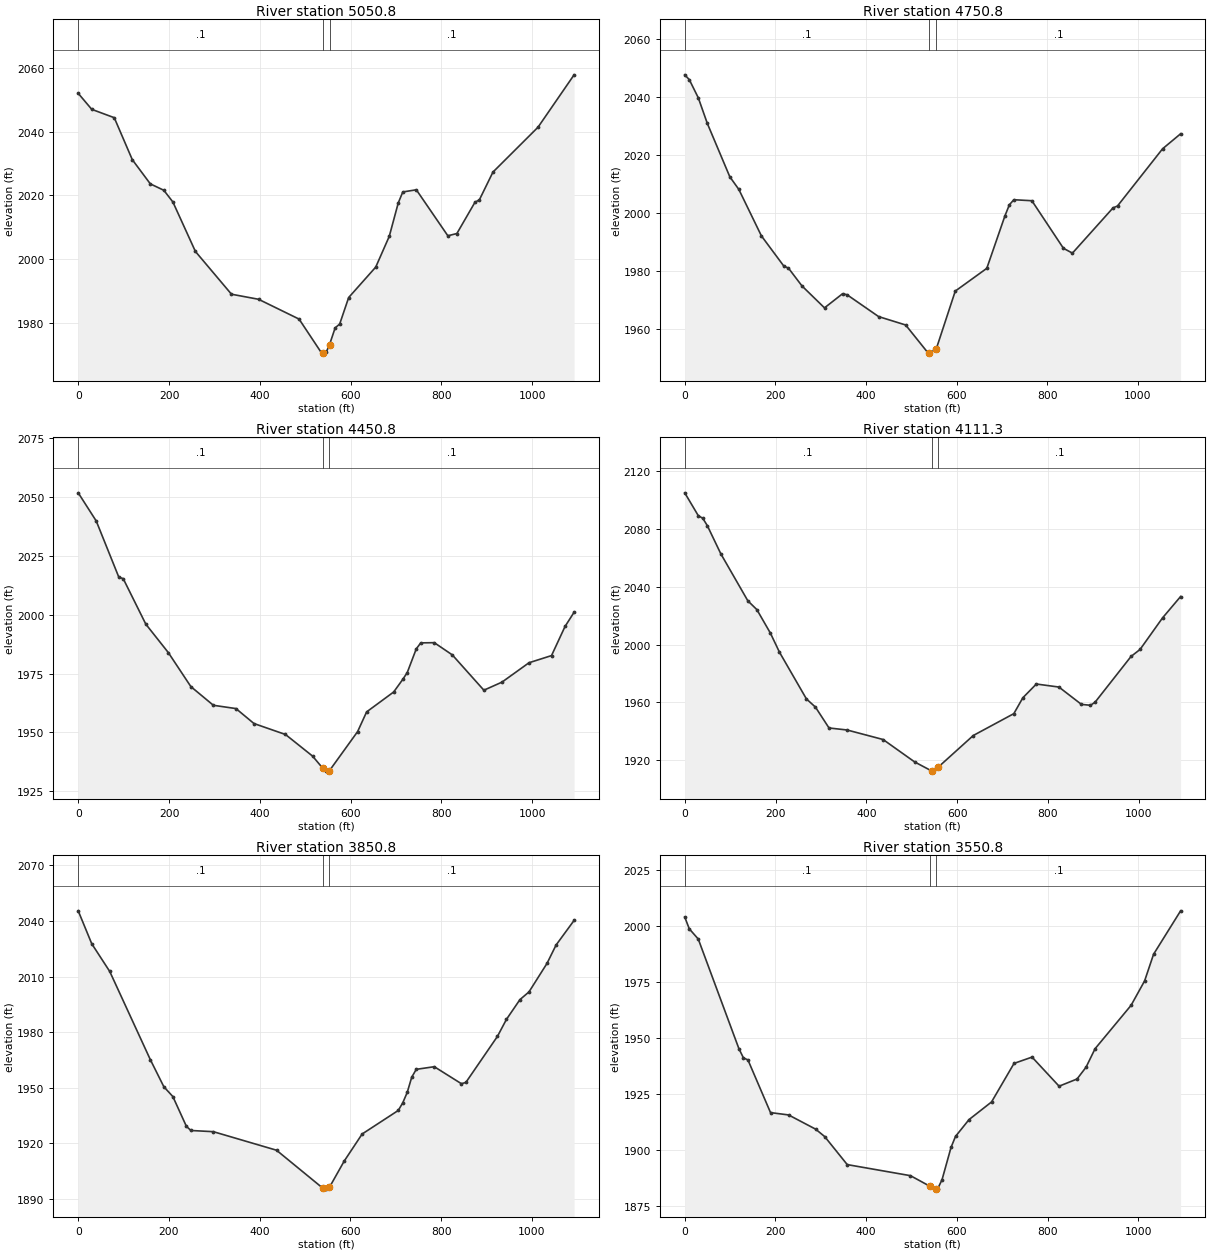
Type RM Length L Ch R = 1 ,5050.8  ,303.2,299.9,299.2
XS GIS Cut Line= 3
     1897833.595       307974.69     1898019.319      308488.132
     1898205.043      309001.574
#Sta/Elev= 30
       0  2052.1    29.8 2047.07    79.4 2044.44   119.1 2031.25   158.8 2023.64
   188.6 2021.62   208.5 2017.94   258.1 2002.39   337.5 1988.95   397.1 1987.36
   486.4 1981.13   536.1 1970.43   538.5 1970.49     546 1970.68   553.5 1973.12
   565.8 1978.37   575.8 1979.58   595.6 1987.91   655.2 1997.48     685 2007.15
   704.8 2017.66   714.8  2021.1   744.6 2021.78     814 2007.32   833.9 2008.03
   873.6 2017.83   883.5 2018.65   913.3 2027.34  1012.6 2041.46    1092 2057.92
#Mann= 3 , 0 , 0
       0      .1       0   538.5    .045       0   553.5      .1       0
Bank Sta=538.5,553.5
XS Rating Curve= 0 ,0
Exp/Cntr=0.3,0.1

Type RM Length L Ch R = 1 ,4750.8  ,298.3,299.9,299.1
XS GIS Cut Line= 3
      1897489.56      308123.812     1897746.509      308607.112
     1897950.209      309114.883
#Sta/Elev= 30
       0 2047.58      10 2045.94    29.9 2039.68    49.8 2030.88    99.5  2012.5
   119.4 2008.16   169.2 1992.18   218.9 1981.74   228.9 1981.09   258.8 1974.95
   308.5 1967.41   348.3 1972.27   358.3 1971.92   427.9 1964.41   487.6 1961.52
   537.4 1951.84   539.9 1951.88   554.9 1953.17   597.1 1973.18   666.7 1981.01
   706.5 1998.96   716.5 2002.87   726.4 2004.61   766.2 2004.27   835.8 1987.91
   855.7 1986.24   945.2 2001.79   955.2 2002.46  1054.7 2022.14  1094.5  2027.3
#Mann= 3 , 0 , 0
       0      .1       0   539.9    .045       0   554.9      .1       0
Bank Sta=539.9,554.9
XS Rating Curve= 0 ,0
Exp/Cntr=0.3,0.1

Type RM Length L Ch R = 1 ,4450.8  ,345.1,339.6,333.9
XS GIS Cut Line= 3
     1897255.043      308224.923     1897473.504      308725.151
     1897689.621      309226.789
#Sta/Elev= 30
       0 2051.68    39.7 2039.73    89.3 2015.96    99.2 2015.24   148.9 1995.96
   198.5 1983.89   248.1 1969.47   297.7 1961.54   347.4 1960.15   387.1  1953.8
   456.5 1949.15   516.1 1939.99   538.4 1934.89   545.8 1933.61   553.4 1933.83
   615.4  1950.4   635.2 1958.74   694.8 1967.19   714.7 1972.51   724.6  1975.4
   744.5 1985.48   754.4 1988.02   784.2 1988.11   823.9 1982.92   893.4 1967.94
   933.2 1971.36   992.8 1979.59  1042.4 1982.63  1072.2    1995  1092.1 2001.02
#Mann= 3 , 0 , 0
       0      .1       0   538.4    .045       0   553.4      .1       0
Bank Sta=538.4,553.4
XS Rating Curve= 0 ,0
Exp/Cntr=0.3,0.1

Type RM Length L Ch R = 1 ,4111.3  ,265.8,260.2,255
XS GIS Cut Line= 3
     1896847.011      308462.242     1897180.198      308894.799
     1897513.625      309327.169
#Sta/Elev= 30
       0 2104.89    29.8 2089.11    39.7 2087.29    49.6 2082.28    79.4 2062.76
     139 2030.19   158.8 2024.15   188.6  2007.9   208.5 1994.76     268 1962.36
   287.9  1956.7   317.7 1942.29   357.4  1940.9   436.8 1934.31   506.3  1918.8
   543.6  1912.6     546 1912.45   558.6 1915.32   635.4 1937.08   724.7  1952.2
   744.6 1963.19   774.3 1972.68     824 1970.59   873.6 1958.59   893.5 1957.99
   903.4 1960.02   982.8 1991.74  1002.7  1996.6  1052.3 2018.46    1092  2033.2
#Mann= 3 , 0 , 0
       0      .1       0   543.6    .045       0   558.6      .1       0
Bank Sta=543.6,558.6
XS Rating Curve= 0 ,0
Exp/Cntr=0.3,0.1

Type RM Length L Ch R = 1 ,3850.8  ,293.8,300,305.7
XS GIS Cut Line= 3
     1896568.332      308734.272     1896996.878      309072.944
     1897420.002      309418.945
#Sta/Elev= 30
       0 2045.44    29.8  2027.7    69.5 2012.74   158.9 1965.21   188.7 1950.59
   208.6 1945.28   238.4 1929.25   248.3    1927   297.9 1926.35     437 1916.36
   538.7 1895.97   546.2 1895.38   553.7 1896.38     586 1910.43   625.7  1925.1
   705.2 1937.78   715.2  1941.9   725.1 1947.56     735 1955.74     745 1959.97
   784.7 1961.39   844.4 1952.23   854.3 1952.91   923.8 1977.71   943.7 1986.91
   973.5 1997.58   993.4 2001.72  1033.2 2017.13    1053 2026.97  1092.8 2040.28
#Mann= 3 , 0 , 0
       0      .1       0   538.7    .045       0   553.7      .1       0
Bank Sta=538.7,553.7
XS Rating Curve= 0 ,0
Exp/Cntr=0.3,0.1

Type RM Length L Ch R = 1 ,3550.8  ,296.4,300,306.6
XS GIS Cut Line= 3
     1896464.727      308842.511     1896786.533      309285.215
      1897108.08      309726.205
#Sta/Elev= 30
       0 2004.02      10 1998.75    29.8  1994.2   119.4  1945.3   129.4 1941.18
   139.3 1940.29   189.1 1916.78   228.9 1915.74   288.6 1909.39   308.5 1906.09
   358.2 1893.59   497.6 1888.65   539.8    1884   554.8 1882.69   557.2 1882.65
   567.2 1886.86     587 1901.25   596.9 1906.17   626.7 1913.67   676.3 1921.53
   725.9 1938.73   765.6 1941.54   825.2 1928.56   864.8 1931.77   884.7 1937.06
   904.5 1945.27   983.9 1964.63  1013.7 1975.52  1033.5 1987.43  1093.1 2006.78
#Mann= 3 , 0 , 0
       0      .1       0   539.8    .045       0   554.8      .1       0
Bank Sta=539.8,554.8
XS Rating Curve= 0 ,0
Exp/Cntr=0.3,0.1

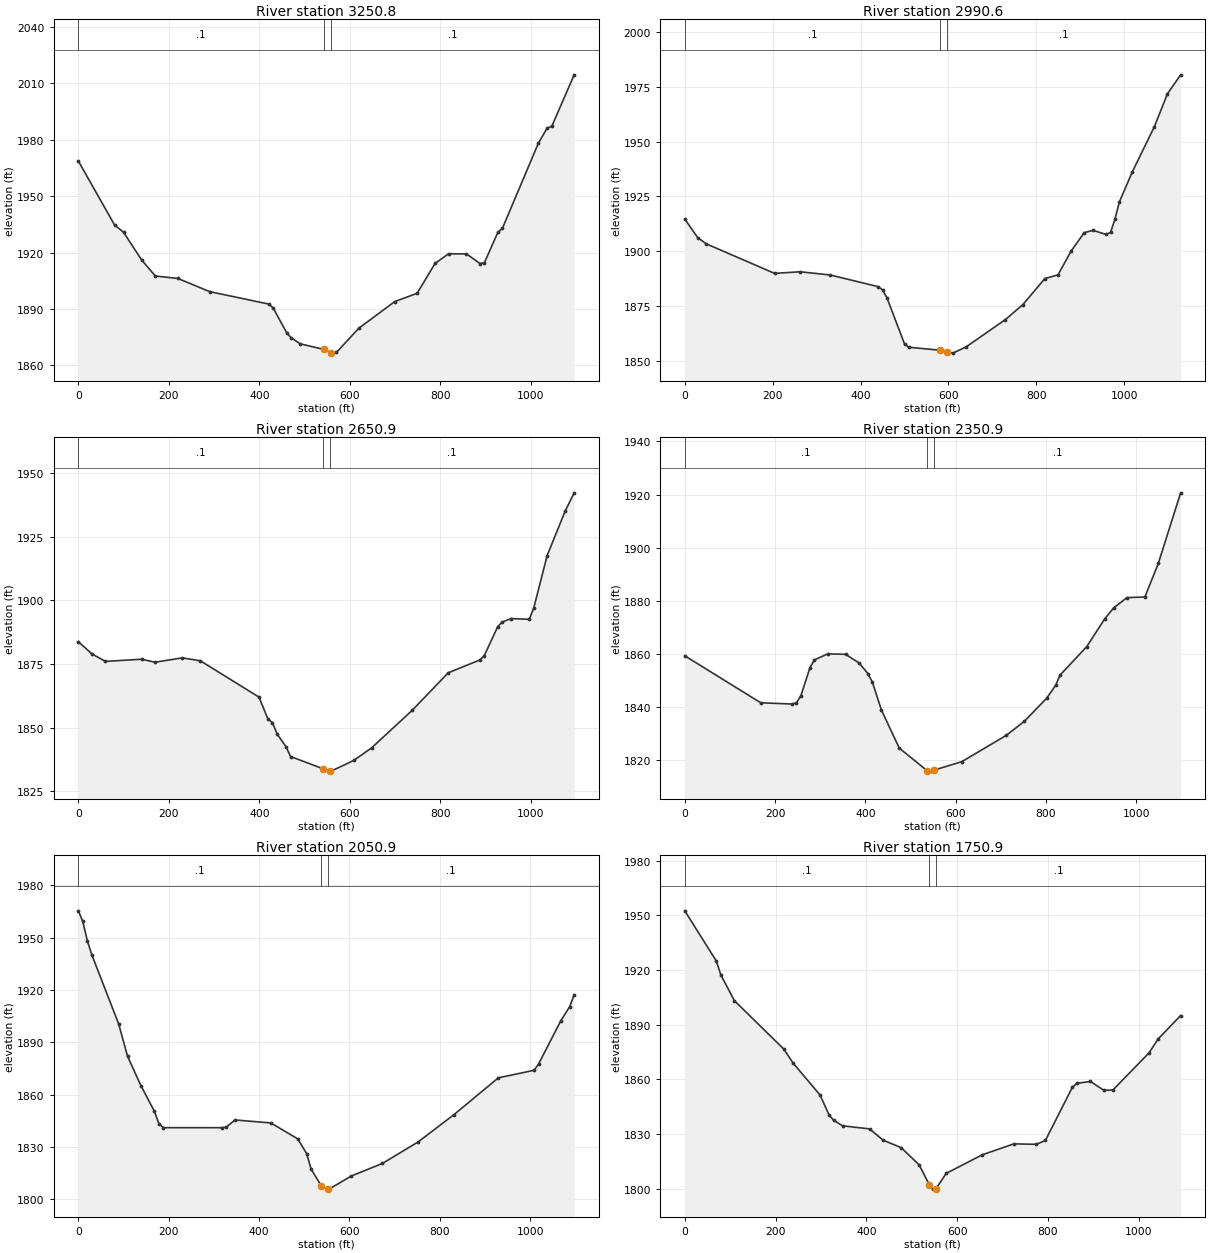
Type RM Length L Ch R = 1 ,3250.8  ,263.5,259.6,252.8
XS GIS Cut Line= 3
     1896289.427      308958.898      1896538.83      309449.411
      1896720.31      309963.568
#Sta/Elev= 30
       0 1968.71      80 1934.69     100 1930.78   140.1 1915.99   170.1 1907.53
   220.1 1906.23   290.2 1899.22   420.2 1892.64   430.2 1890.67   460.2 1877.41
   470.2  1874.7   490.2 1871.48   542.8 1868.48   557.8 1866.74   560.2 1866.52
   570.1 1866.86   619.7 1879.77     699 1893.93   748.6 1898.34   788.2 1914.24
   817.9 1919.35   857.6  1919.3   887.3 1914.18   897.2  1914.6     927  1930.8
   936.9 1932.84  1016.2 1978.03    1036 1986.29    1046 1987.12  1095.5 2014.53
#Mann= 3 , 0 , 0
       0      .1       0   542.8    .045       0   557.8      .1       0
Bank Sta=542.8,557.8
XS Rating Curve= 0 ,0
Exp/Cntr=0.3,0.1

Type RM Length L Ch R = 1 ,2990.6  ,340.9,339.9,338.8
XS GIS Cut Line= 3
     1895861.252      309231.475     1896163.825      309365.397
     1896636.352      310008.255
#Sta/Elev= 30
       0 1914.64    29.2 1906.24    48.7 1903.36   204.4 1889.84   262.8 1890.58
   330.9 1889.11   440.6 1883.76   450.6  1882.2   460.5 1878.52   500.4 1857.46
   510.4 1856.06   581.8 1854.69   596.8 1853.96   610.1 1853.38     640 1856.18
   729.8 1868.72   769.7 1875.58   819.6 1887.47   849.5 1889.15   879.4 1900.04
   909.3 1908.47   929.3 1909.53   959.2 1907.62   969.2  1908.6   979.1 1914.52
   989.1 1922.43    1019 1936.38  1068.9  1956.9  1098.8 1971.97  1128.7 1980.62
#Mann= 3 , 0 , 0
       0      .1       0   581.8    .045       0   596.8      .1       0
Bank Sta=581.8,596.8
XS Rating Curve= 0 ,0
Exp/Cntr=0.3,0.1

Type RM Length L Ch R = 1 ,2650.9  ,307.6,300,294.5
XS GIS Cut Line= 3
     1895718.449      309347.094     1896056.816      309779.294
     1896397.553      310207.079
#Sta/Elev= 30
       0 1883.77    29.9 1878.99    59.9 1876.02   139.7 1876.87   169.7  1875.7
   229.5  1877.4   269.5 1876.27   399.2 1861.99   419.2 1853.29   429.1 1851.96
   439.1 1847.54   459.1 1842.43   469.1 1838.62   541.4 1833.77   556.4 1832.96
   558.8 1832.88   608.6 1837.08   648.3 1842.04   737.8 1856.77   817.4 1871.53
     887 1876.56   896.9 1878.18   926.8 1889.66   936.7 1891.49   956.6 1892.85
   996.4 1892.56  1006.3 1896.86  1036.1 1917.62  1075.9 1935.09  1095.8 1942.29
#Mann= 3 , 0 , 0
       0      .1       0   541.4    .045       0   556.4      .1       0
Bank Sta=541.4,556.4
XS Rating Curve= 0 ,0
Exp/Cntr=0.3,0.1

Type RM Length L Ch R = 1 ,2350.9  ,307.7,300,291.7
XS GIS Cut Line= 3
     1895377.507      309678.107     1895835.855      309972.129
     1896274.941      310310.325
#Sta/Elev= 30
       0 1859.17   168.3 1841.45   237.6 1840.98   247.5 1841.45   257.4 1844.16
   277.2  1854.6   287.1 1857.63   316.8 1859.89   356.4 1859.73   386.1 1856.49
   405.9 1852.44   415.8 1849.21   435.6 1838.78   475.2 1824.38     537 1815.84
   544.6 1815.67     552 1816.04   613.8 1819.23   712.8  1829.2   752.4 1834.44
   801.9 1843.17   821.7 1847.99   831.6 1851.88   890.9 1862.67   930.5 1873.08
   950.3 1877.22     980 1881.12  1019.6 1881.35  1049.3 1893.99  1098.8 1920.64
#Mann= 3 , 0 , 0
       0      .1       0     537    .045       0     552      .1       0
Bank Sta=537,552
XS Rating Curve= 0 ,0
Exp/Cntr=0.3,0.1

Type RM Length L Ch R = 1 ,2050.9  ,301.9,300,296.6
XS GIS Cut Line= 3
     1895170.905      310115.427     1895701.485      310239.141
     1896230.881      310396.344
#Sta/Elev= 30
       0 1965.34     9.9 1959.27    19.8 1948.25    29.7 1940.21    89.2 1900.52
     109 1881.86   138.7 1864.99   168.4 1850.36   178.3 1843.25   188.2    1841
     317 1840.99   326.9 1841.26   346.7 1845.43   425.9 1843.72   485.4  1834.6
   505.2 1826.12   515.1 1817.21   537.3 1807.75   552.3 1805.82   554.7 1805.76
     604 1813.28     673 1820.51   751.9 1832.83   830.8  1848.4   929.4 1869.59
  1008.3  1873.9  1018.2 1877.44  1067.5 1902.26  1087.2 1910.39  1097.1  1917.2
#Mann= 3 , 0 , 0
       0      .1       0   537.3    .045       0   552.3      .1       0
Bank Sta=537.3,552.3
XS Rating Curve= 0 ,0
Exp/Cntr=0.3,0.1

Type RM Length L Ch R = 1 ,1750.9  ,299.4,300,300.6
XS GIS Cut Line= 3
     1895123.943      310459.225     1895664.457      310536.429
     1896204.971      310613.634
#Sta/Elev= 30
       0 1952.49    69.5 1924.91    79.4 1917.29   109.2 1903.17   218.4  1876.5
   238.2 1868.98   297.8  1851.4   317.7 1840.44   327.6 1837.51   347.4 1834.46
     407 1832.76   436.8 1826.57   476.5 1822.48   516.2 1812.99   538.5 1802.11
     546 1799.69   553.5 1800.02   575.8 1808.36   655.2 1818.55   724.7 1824.54
   774.3 1824.29   794.2 1826.41   853.8 1855.72   863.7 1857.78   893.4  1858.8
   923.2  1853.9   943.1 1854.17  1022.5 1874.53  1042.4 1882.12    1092 1895.01
#Mann= 3 , 0 , 0
       0      .1       0   538.5    .045       0   553.5      .1       0
Bank Sta=538.5,553.5
XS Rating Curve= 0 ,0
Exp/Cntr=0.3,0.1

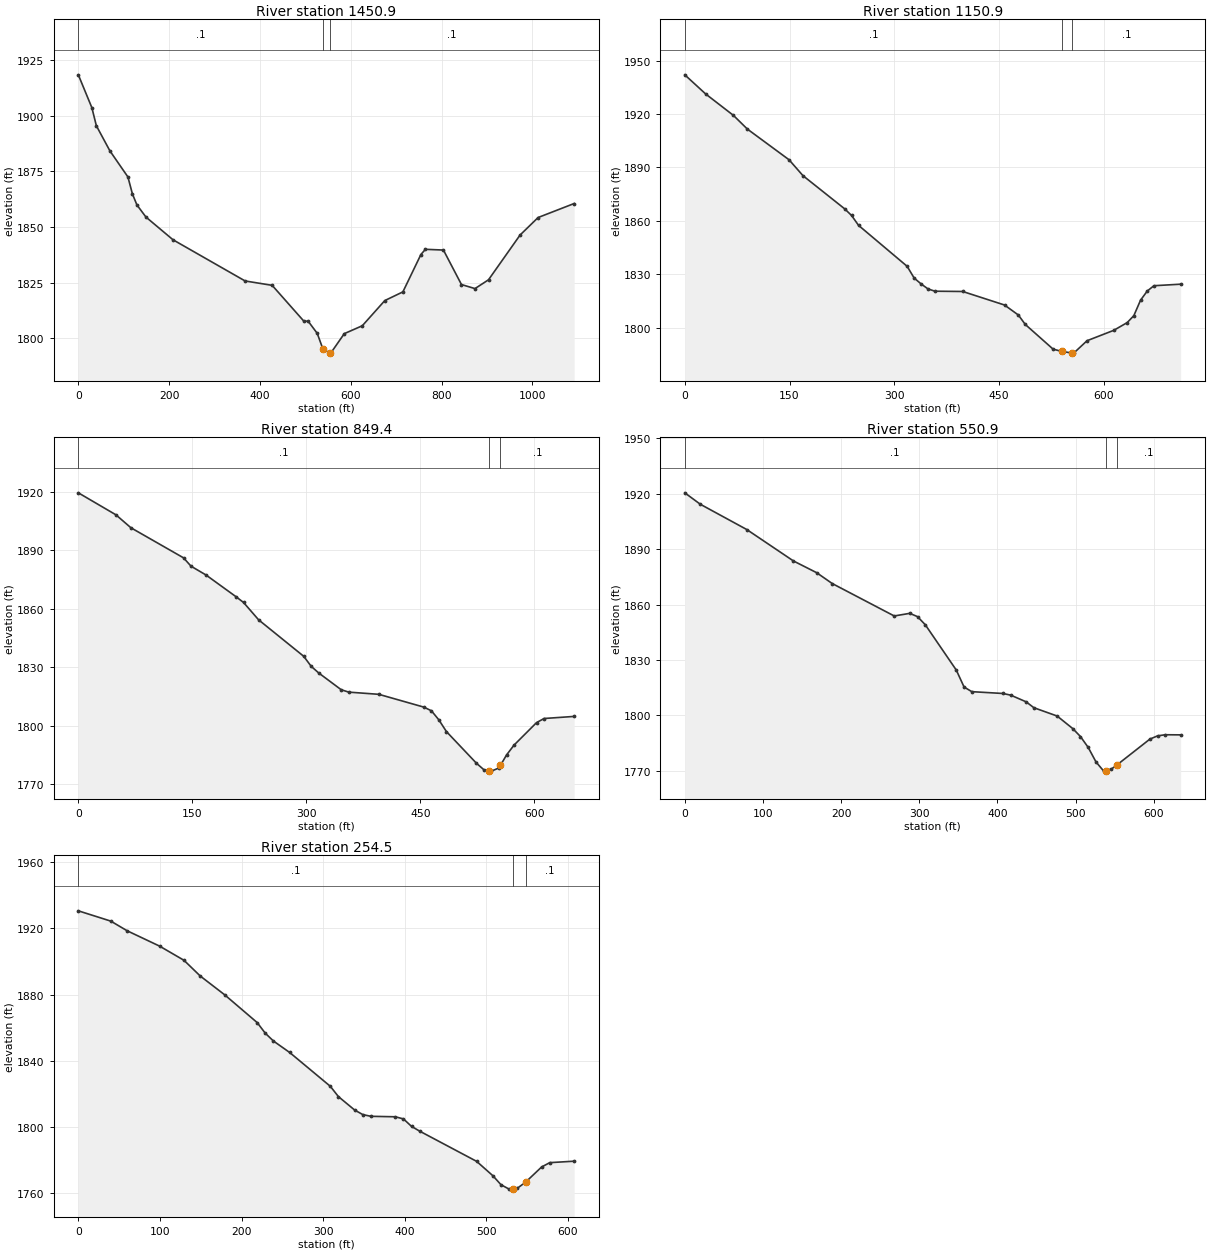
Type RM Length L Ch R = 1 ,1450.9  ,300.3,300,299.2
XS GIS Cut Line= 3
     1895083.305      310741.154      1895621.48      310833.263
     1896159.655      310925.372
#Sta/Elev= 30
       0 1918.38    29.8 1903.62    39.7  1895.5    69.5 1884.22   109.2 1872.49
   119.1 1864.88     129 1859.92   148.9 1854.47   208.5 1844.26   367.3 1825.75
   426.9 1823.78   496.4 1807.75   506.3 1807.63   526.2 1802.19   538.5 1795.26
   553.5 1793.34   555.9 1793.32   585.7 1802.07   625.4 1805.62     675 1816.94
   714.8 1820.84   754.5 1837.64   764.4 1839.97   804.1 1839.64   843.8 1824.14
   873.6 1822.32   903.4 1826.28   972.9 1846.39  1012.6 1854.26    1092 1860.55
#Mann= 3 , 0 , 0
       0      .1       0   538.5    .045       0   553.5      .1       0
Bank Sta=538.5,553.5
XS Rating Curve= 0 ,0
Exp/Cntr=0.3,0.1

Type RM Length L Ch R = 1 ,1150.9  ,296.8,301.6,306.8
XS GIS Cut Line= 3
     1895048.816       311047.65     1895589.661      311131.496
     1895750.901      311153.549
#Sta/Elev= 30
       0    1942    29.8 1931.28    69.7  1919.2    89.6 1911.54   149.3  1894.3
   169.2 1885.38   228.9 1866.76   238.8 1863.03   248.8 1857.48   318.4 1834.47
   328.4 1827.91   338.3 1824.61   348.3 1821.77   358.2  1820.5     398 1820.34
   457.8 1812.75   477.6 1807.14   487.6 1801.82   527.4 1787.97   539.8 1786.69
   554.8 1785.78   556.9 1785.73     576  1792.7   614.3 1798.54   633.5 1802.87
     643 1806.77   652.6 1815.44   662.2  1820.6   671.8 1823.58     710 1824.44
#Mann= 3 , 0 , 0
       0      .1       0   539.8    .045       0   554.8      .1       0
Bank Sta=539.8,554.8
XS Rating Curve= 0 ,0
Exp/Cntr=0.3,0.1

Type RM Length L Ch R = 1 ,849.4   ,297.2,298.4,299.7
XS GIS Cut Line= 2
     1895004.164      311227.293     1895613.259      311460.869
#Sta/Elev= 30
       0 1919.51    49.4 1908.25    69.2 1901.59   138.4 1886.17   148.3 1881.88
     168 1877.37   207.6  1866.2   217.4 1863.27   237.2 1854.38   296.5 1835.69
   306.4 1830.53   316.3 1827.12   345.9 1818.52   355.8  1817.3   395.4 1816.17
   454.7  1809.6   464.6 1807.72   474.4 1803.06   484.3 1797.08   523.8 1780.84
   533.7 1777.46   540.4    1777   543.6 1776.78   553.5 1778.43   555.4  1779.7
   563.4 1785.04   573.3 1790.13   602.9 1801.65   612.8 1803.77   652.4 1804.84
#Mann= 3 , 0 , 0
       0      .1       0   540.4    .045       0   555.4      .1       0
Bank Sta=540.4,555.4
XS Rating Curve= 0 ,0
Exp/Cntr=0.3,0.1

Type RM Length L Ch R = 1 ,550.9   ,296.2,296.4,296.4
XS GIS Cut Line= 3
      1894896.21      311474.143     1895394.952      311696.343
     1895475.618       311732.79
#Sta/Elev= 30
       0 1920.52    19.8 1914.35    79.4 1900.63     139 1883.65   168.8 1877.28
   188.6 1871.44     268 1853.87   287.9 1855.29   297.8 1853.51   307.8 1849.09
   347.4  1824.6   357.4  1815.4   367.3  1812.9     407 1811.92     417 1811.03
   436.8  1807.4   446.7 1804.21   476.5 1799.71   496.4 1792.94   506.3 1788.62
   516.2 1782.74   526.2 1774.87   536.1 1769.89   538.5 1770.17     546 1771.05
   553.5  1773.4   595.2 1787.23     605 1788.98   614.8 1789.58   634.5 1789.52
#Mann= 3 , 0 , 0
       0      .1       0   538.5    .045       0   553.5      .1       0
Bank Sta=538.5,553.5
XS Rating Curve= 0 ,0
Exp/Cntr=0.3,0.1

Type RM Length L Ch R = 1 ,254.5   ,239.4,254.5,251.9
XS GIS Cut Line= 2
     1894779.891      311742.619      1895333.23      311993.834
#Sta/Elev= 30
       0 1930.52    39.8 1924.31    59.8 1918.49    99.6 1909.22   129.5 1900.67
   149.4 1891.19   179.3 1879.87   219.2 1863.08   229.1 1856.68   239.1 1851.97
     259 1845.05   308.8 1824.65   318.8  1818.4   338.7 1810.29   348.7 1807.55
   358.6 1806.52   388.5 1806.24   398.5 1804.94   408.4 1800.44   418.4 1797.56
   488.2 1779.33   508.1 1770.65     518 1765.25     528 1762.58   533.1 1762.84
     538 1763.09   548.1 1766.75   567.8 1775.94   577.8 1778.56   607.7 1779.44
#Mann= 3 , 0 , 0
       0      .1       0   533.1    .045       0   548.1      .1       0
Bank Sta=533.1,548.1
XS Rating Curve= 0 ,0
Exp/Cntr=0.3,0.1